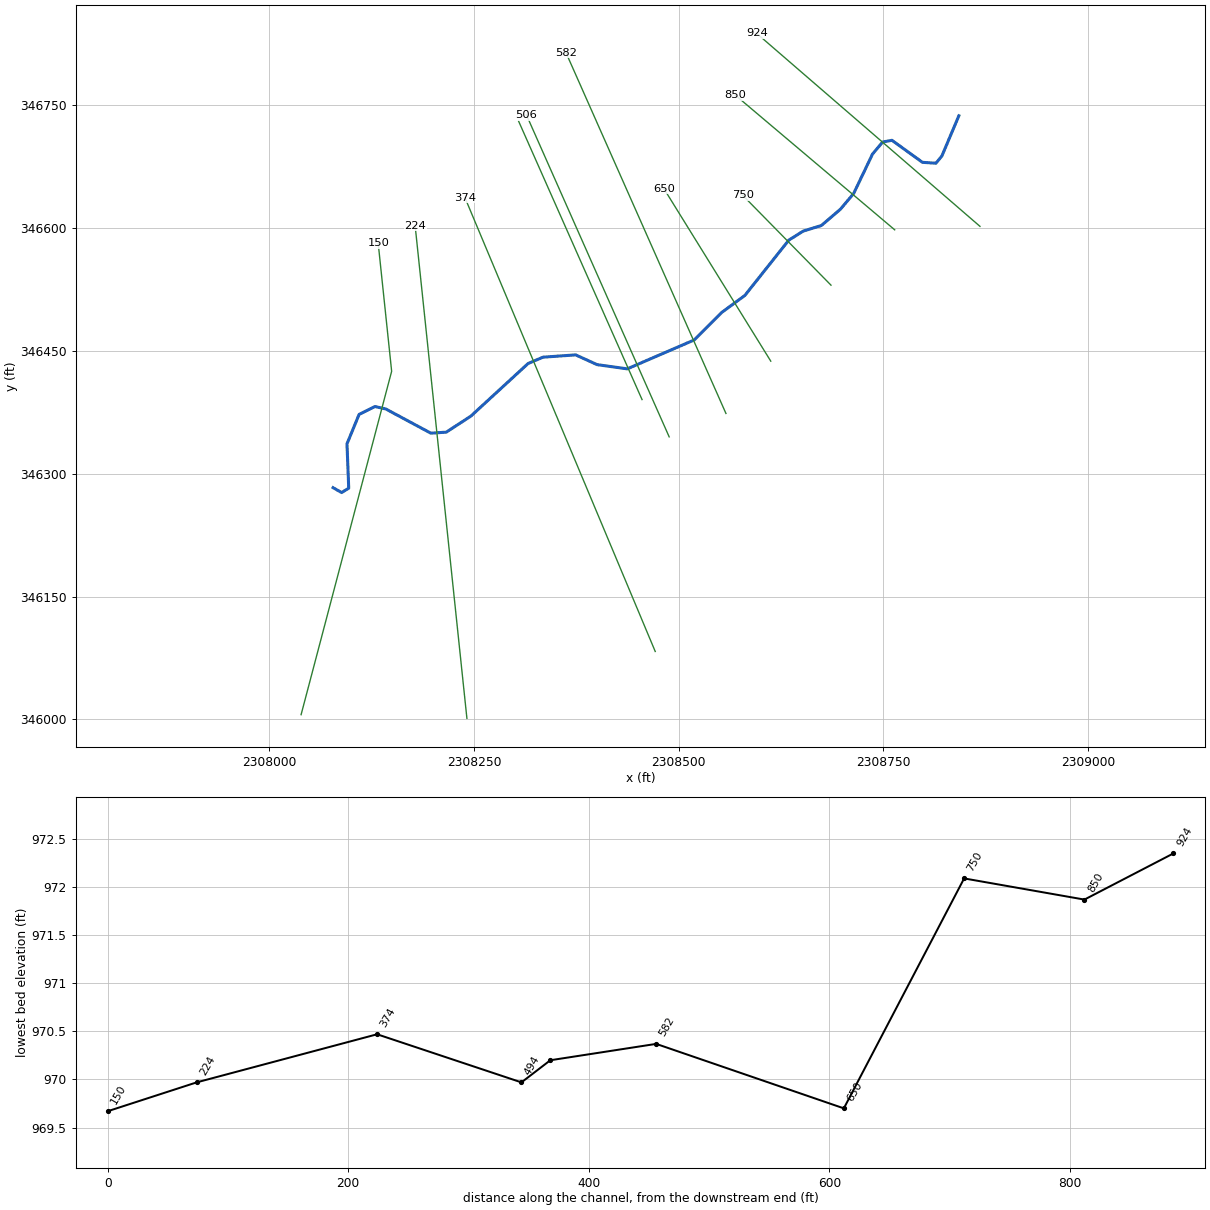
--- CAR-542-1263Exist.prj (project) ---

Proj Title=CAR-542-1263 Exist
Current Plan=p02
Current HD=h01
Default Exp/Contr=0.3,0.1
English Units
Geom File=g02
Flow File=f01
Plan File=p02
HD File=h01
Y Axis Title=Elevation
X Axis Title(PF)=Main Channel Distance
X Axis Title(XS)=Station
BEGIN DESCRIPTION:
END DESCRIPTION:
DSS Export Rating Curves= 0
DSS Export Rating Curve Sorted= 0
DSS Export Volume Flow Curves= 0
DXF Filename=..\..\Existing Bridge\Stream12.65Exist\Stream12CAD.
DXF OffsetX= 0
DXF OffsetY= 0
DXF ScaleX= 1
DXF ScaleY= 10

--- CAR-542-1263Exist.p02 (plan) ---

Plan Title=Stream 12.65
Program Version=4.10
Short Identifier=Plan 02
Geom File=g02
Flow File=f01
Subcritical Flow
K Sum by GR= 0
Std Step Tol= 0.01
Critical Tol= 0.01
Num of Std Step Trials= 20
Max Error Tol= 0.3
Flow Tol Ratio= 0.001
Split Flow NTrial= 30
Split Flow Tol= 0.02
Split Flow Ratio= 0.02
Log Output Level= 0
Friction Slope Method= 1
Unsteady Friction Slope Method= 2
Unsteady Bridges Friction Slope Method= 1
Parabolic Critical Depth
Global Vel Dist= 0 , 0 , 0
Global Log Level= 0
CheckData=True
Encroach Param=-1 ,0,0, 0
Computation Interval=1HOUR
Output Interval=1HOUR
Run HTab= 0
Run UNet= 0
Run PostProcess= 0
Run WQNet= 0
UNET Theta= 1
UNET Theta Warmup= 1
UNET ZTol= 0.02
UNET ZSATol= 0.05
UNET MxIter= 20
UNET MaxInSteps= 0
UNET DtIC= 0
UNET DtMin= 0
UNET MaxCRTS= 20
UNET WFStab= 2
UNET SFStab= 1
UNET WFX= 1
UNET SFX= 1
UNET DSS MLevel= 4
UNET DZMax Abort= 100
UNET Convert EG Bridges= 0
UNET Use Existing IB Tables=-1
UNET Froude Reduction=False
UNET Froude Limit= 1
UNET Froude Power= 10
UNET Time Slicing=0,0, 5
UNET Junction Losses=0
Instantaneous Interval=1HOUR
Write IC File= 0
Write IC File at Sim End=0
Echo Input=False
Echo Parameters=False
Echo Output=False
Write Detailed= 0
WQ AD Non Conservative
WQ ULTIMATE=-1
WQ Max Comp Step=1HOUR
WQ Output Interval=15MIN
WQ Output Selected Increments= 0
WQ Output face flow=0
WQ Output face velocity=0
WQ Output face area=0
WQ Output face dispersion=0
WQ Output cell volume=0
WQ Output cell surface area=0
WQ Output cell continuity=0
WQ Output cumulative cell continuity=0
WQ Output face conc=0
WQ Output face dconc_dx=0
WQ Output face courant=0
WQ Output face peclet=0
WQ Output face adv mass=0
WQ Output face disp mass=0
WQ Output cell mass=0
WQ Output cell source sink temp=0
WQ Output cell source sink nsm=0
WQ Output MaxMinRange=-1
WQ Daily Max Min Mean=-1
WQ Daily Range=0
WQ Daily Time=0
WQ Create Restart=0
WQ Fixed Restart=0
WQ System Summary=0
WQ Use Fixed Temperature=0
Sorting and Armoring Iterations= 10
XS Update Threshold= 0.02
Hydraulics Update Threshold= 0.02
Energy Slope Method= 1
Volume Change Method= 0
XS Weighting Method= 0
Number of US Weighted Cross Sections= 1
Number of DS Weighted Cross Sections= 1
Upstream XS Weight=0.25
Main XS Weight=0.5
Downstream XS Weight=0.25
Number of DS XS's Weighted with US Boundary= 1
Upstream Boundary Weight= 1
Weight of XSs Associated with US Boundary= 0
Number of US XS's Weighted with DS Boundary= 1
Downstream Boundary Weight= 0.5
Weight of XSs Associated with DS Boundary= 0.5
Sediment Output Level= 4
Mass or Volume Output= 0
Output Increment Type= 1
Profile and TS Output Increment= 10
XS Output Flag= 0
XS Output Increment= 10
Disregard all LS=0
Disregard all Conn=0
Disregard all Breaches=0
Disregard all Pumps=0

--- CAR-542-1263Exist.f01 (steady flow) ---

Flow Title=Stream12.65
Program Version=4.10
Number of Profiles= 4
Profile Names=10 Year,25 Year,50 Year,100 Year
River Rch & RM=Huff Run,Huff Run        ,924
     600     760     874     988
Boundary for River Rch & Prof#=Huff Run,Huff Run        , 1
Up Type= 0
Dn Type= 3
Dn Slope=0.0035
Boundary for River Rch & Prof#=Huff Run,Huff Run        , 2
Up Type= 0
Dn Type= 3
Dn Slope=0.0035
Boundary for River Rch & Prof#=Huff Run,Huff Run        , 3
Up Type= 0
Dn Type= 3
Dn Slope=0.0035
DSS Import GetInterval= 0
DSS Import GetPeak= 0
DSS Import FillOption= 0

--- CAR-542-1263Exist.g02 (geometry) ---

Geom Title=Stream12.65
Program Version=4.10

River Reach=Huff Run        ,Huff Run
Reach XY= 30
      2308842.06       346737.19      2308821.31       346688.07
      2308814.02       346679.22      2308797.57       346680.34
      2308760.36       346707.22      2308749.03       346705.19
      2308736.63       346690.46      2308713.55       346642.21
      2308697.34       346622.99      2308674.17       346603.18
      2308651.94       346596.34      2308634.28       346585.22
      2308580.66       346517.71      2308552.54       346497.06
      2308518.92       346463.41      2308437.06       346428.08
      2308400.24        346433.2      2308373.98       346445.14
      2308334.18       346442.33      2308315.95       346434.63
       2308246.1        346370.4        2308216.       346350.76
      2308197.12       346349.53      2308142.11       346379.09
       2308128.9       346382.08      2308109.51       346372.42
      2308094.72       346336.48      2308096.84       346282.38
      2308088.21       346276.97      2308077.72       346282.96

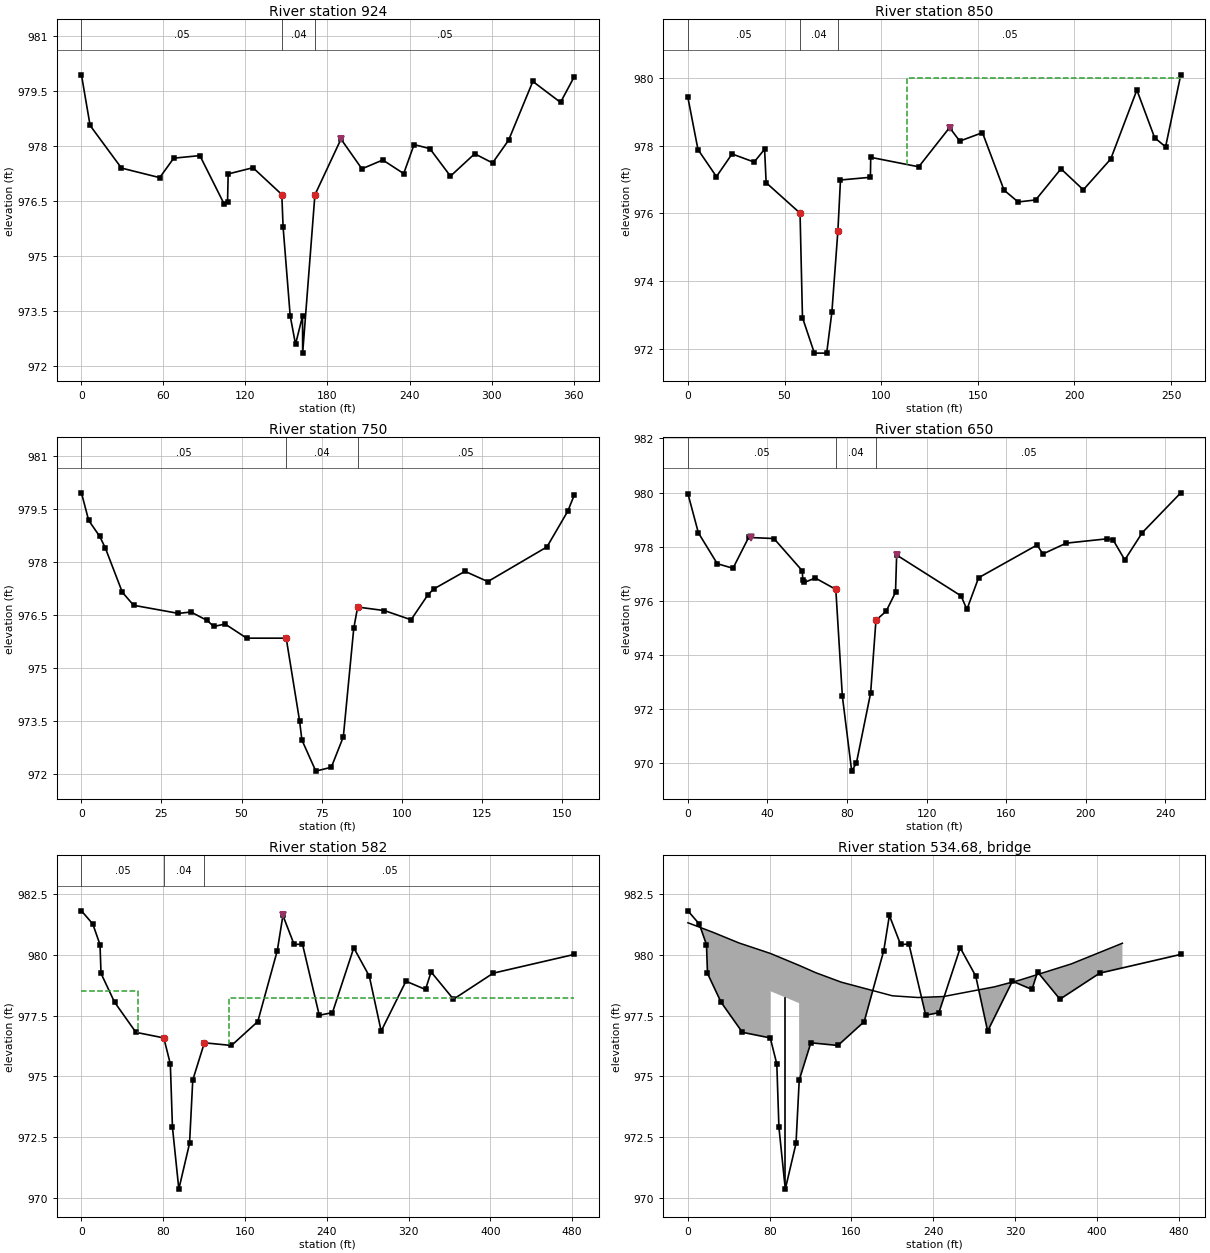
Type RM Length L Ch R = 1 ,924     ,73.9755,74,75.1076
XS GIS Cut Line= 3
2308867.85220086 346602.103113452308748.80630776 346704.98100066
2308595.05712275 346837.84901401
#Sta/Elev= 30
       0  979.936.349976  978.5529.28998  977.39   57.25  977.1367.51999  977.66
86.63998  977.73  104.55   976.4  106.88  976.46107.3431  977.23125.4831   977.4
146.5831  976.67147.5131  975.79152.7031  973.37156.6131  972.59161.7431  973.36
161.8331  972.35170.7931  976.66  189.87  978.18  205.17  977.37  220.46  977.61
  235.75  977.24  243.33  978.03  254.87  977.92  269.95  977.17  287.67  977.78
  300.75  977.53  312.49  978.15  330.21  979.75  350.46  979.18  360.55  979.88
#Mann= 3 , 0 , 0
       0     .05       0146.5831     .04       0170.7931     .05       0
Levee=0,,,-1,189.87,978.18,,
Bank Sta=146.5831,170.7931
XS Rating Curve= 0 ,0
Exp/Cntr=0.3,0.1

Type RM Length L Ch R = 1 ,850     ,99.39639,100,98.1405
XS GIS Cut Line= 3
2308763.69126296346597.8893159712308712.60768168346641.053295127
2308568.90570207346762.476834678
#Sta/Elev= 30
       0  979.435.209991  977.8914.75999  977.09   22.83  977.7634.26999  977.52
39.68001   977.9 40.4812  976.91 58.0212  976.01 59.2812  972.92 65.4412  971.87
 71.8012  971.87 74.4912  973.08 77.6112  975.49 78.9412  976.99 94.4212  977.07
   94.59  977.66  119.43  977.38  135.39  978.54  140.66  978.14   152.4  978.39
  163.57  976.69  170.87  976.34  179.94   976.4  193.03  977.32  204.58   976.7
  218.77  977.61   232.3  979.65  241.49  978.24  247.15  977.97  255.01   980.1
#Mann= 3 , 0 , 0
       0     .05       0 58.0212     .04       0 77.6112     .05       0
Levee=0,,,-1,135.39,978.54,,
#XS Ineff= 2 , 0
       0                  113.39       0     980
Permanent Ineff=
       F       F
Bank Sta=58.0212,77.6112
XS Rating Curve= 0 ,0
Exp/Cntr=0.3,0.1

Type RM Length L Ch R = 1 ,750     ,101.5829,100,97.0342
XS GIS Cut Line= 3
2308685.86915578346530.3059815172308633.06877957346584.038334386
2308577.99683635346640.082349571
#Sta/Elev= 29
       0  979.96 2.26001  979.185.699997  978.737.460007   978.412.76001  977.15
   16.28  976.78    30.3  976.5534.17001  976.59   39.29  976.35    41.3  976.18
   44.87  976.25 51.5935  975.85 63.9435  975.85 68.1235  973.51 68.8435  972.97
 73.1935  972.09 78.0335   972.2 81.7835  973.06 85.0435  976.13 86.2535  976.73
 94.6135  976.63  102.93  976.37  108.23  977.08     110  977.24  119.77  977.74
   126.9  977.45  145.36  978.43  151.87  979.44  153.91   979.9
#Mann= 3 , 0 , 0
       0     .05       0 63.9435     .04       0 86.2535     .05       0
Bank Sta=63.9435,86.2535
XS Rating Curve= 0 ,0
Exp/Cntr=0.3,0.1

Type RM Length L Ch R = 1 ,650     ,159.1537,156,152.7028
XS GIS Cut Line= 3
2308612.32390113346437.4798121452308567.67302726346509.560090087
2308481.80453818346648.178307909
#Sta/Elev= 30
       0  979.965.270004  978.51   14.77  977.3722.67001   977.230.54001  978.34
43.26001   978.357.49001  977.11 57.7998  976.77 58.6298  976.68 64.0698  976.84
 74.3798  976.42 77.6698  972.47 82.3698   969.7 84.7398     970 91.8898  972.59
 94.5698  975.28 99.6798  975.61104.3998  976.31  104.97  977.69  137.36  976.18
   140.3  975.68  146.18  976.85  175.59  978.06  178.53  977.73  190.29  978.13
  210.88  978.29  213.82  978.25   219.7  977.51  228.52  978.52  247.85  979.99
#Mann= 3 , 0 , 0
       0     .05       0 74.3798     .04       0 94.5698     .05       0
Levee=-1,31.49,978.36,-1,104.97,977.69,,
Bank Sta=74.3798,94.5698
XS Rating Curve= 0 ,0
Exp/Cntr=0.3,0.1

Type RM Length L Ch R = 1 ,582     ,87.12,88,88.9652
XS GIS Cut Line= 3
2308557.57716656346373.5998388312308517.98921219346462.888579781
2308362.18554517346814.296311911
#Sta/Elev= 30
       0   981.811.10001  981.2618.17001  980.41 19.1546  979.23 32.3846  978.05
 53.2746  976.81 80.5646  976.58 86.9546  975.51 89.0246  972.91 95.2646  970.37
105.7446  972.25108.8846  974.85120.2446  976.38146.7546  976.27172.4546  977.25
191.5946  980.17197.0646  981.61208.0046  980.42216.2146  980.43232.6146  977.51
245.5346  977.62266.3746  980.28281.5346  979.12293.1746  976.86317.3946  978.91
336.5346  978.57342.0046  979.29363.8846  978.17402.7946  979.24482.0746  980.01
#Mann= 3 , 0 , 0
       0     .05       0 80.5646     .04       0120.2446     .05       0
Levee=0,,,-1,197.06,981.61,,
#XS Ineff= 2 , 0
       0    55.3   978.5  143.85       0  978.24
Permanent Ineff=
       F       F
Bank Sta=80.5646,120.2446
XS Rating Curve= 0 ,0
Exp/Cntr=0.5,0.3

Type RM Length L Ch R = 3 ,534.68  ,,,
Bridge Culvert--1,0,-1,-1, 0
Deck Dist Width WeirC Skew NumUp NumDn MinLoCord MaxHiCord MaxSubmerge Is_Ogee
33,30,2.6,0, 14, 14, , , 0.95, 0, 0,0,,
       0      25      50   80.68  108.74     125     150     200     225     250
     300     325     375     425
  981.31  980.91  980.48  980.05  979.56  979.26  978.87  978.31  978.24  978.28
  978.68  978.96  979.62  980.47
       0       0       0   978.5  978.01       0       0       0       0       0
       0       0       0       0
       0      25      50   80.68  108.74     125     150     200     225     250
     300     325     375     425
  981.31  980.91  980.48  980.05  979.56  979.26  978.87  978.31  978.24  978.28
  978.68  978.96  979.62  980.47
       0       0       0   978.5  978.01       0       0       0       0       0
       0       0       0       0
Pier Skew, UpSta & Num, DnSta & Num=  ,94.71, 2 ,94.71, 2 , 0 , 0 , 0 ,,
   1.366   1.366
       0   979.5
   1.366   1.366
       0   979.5
BR Coef=-1 , 0 , 0 ,, 0 ,,,0.8,-1,,0,
WSPro=,,,, 1 ,,,, 0 ,,,, 0 ,,,,-1 ,-1 ,-1 , 0 , 0 , 0 , 0 , 0
BC Design=,, 0 ,, 0 ,,,,,,
BC Use User HTab Curves=0
BC User HTab FreeFlow(D)= 0

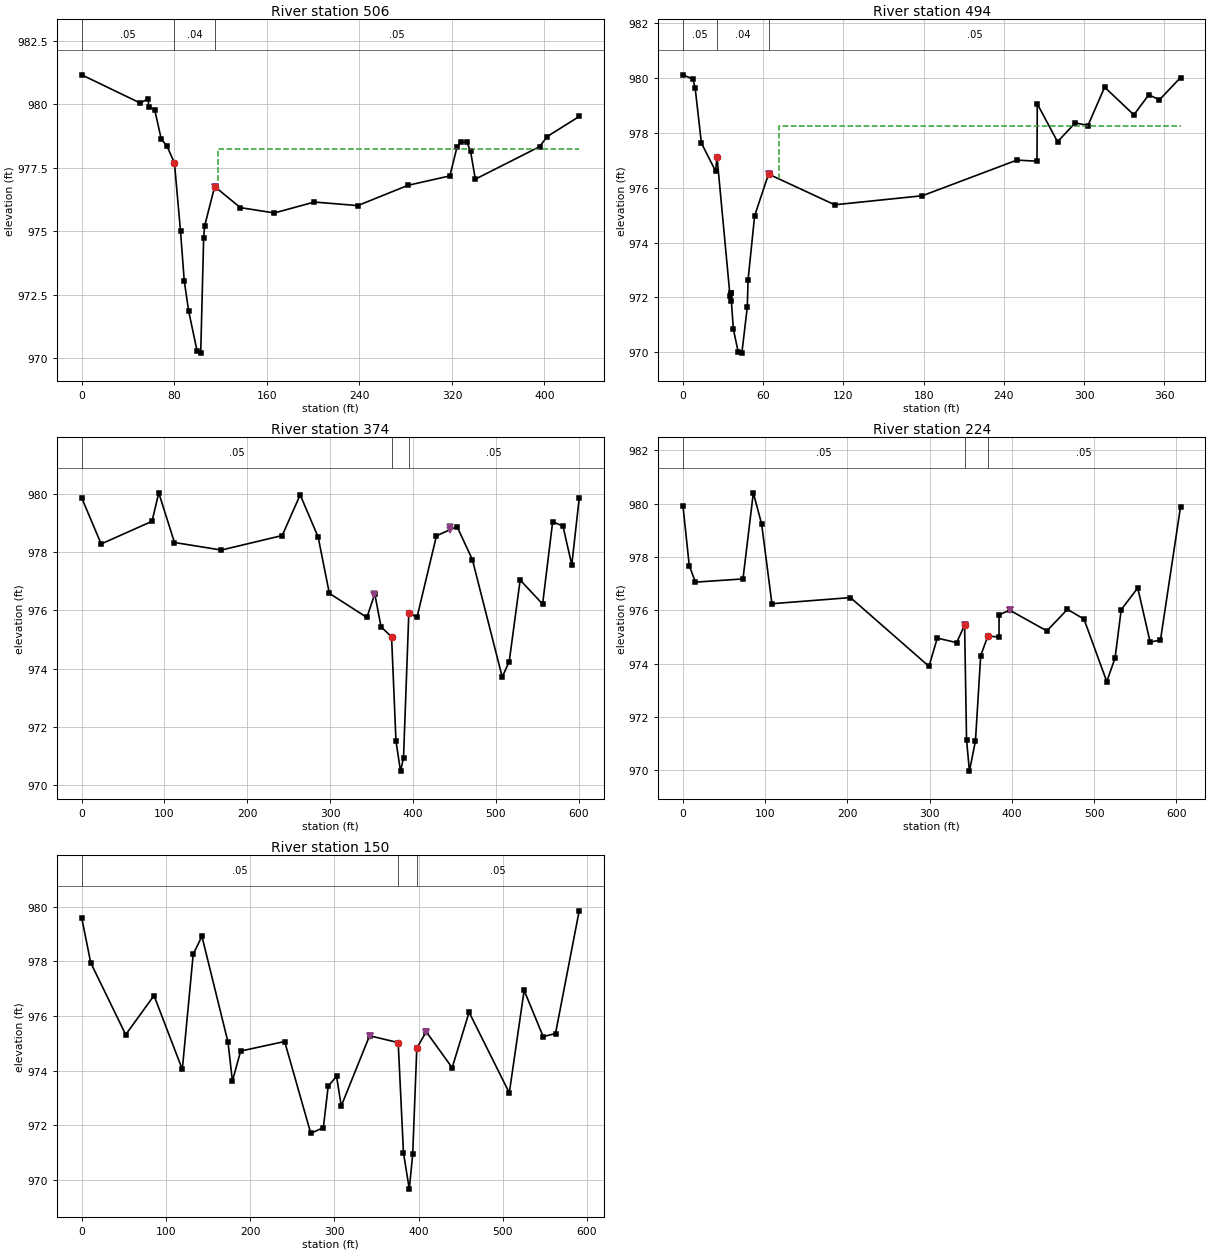
Type RM Length L Ch R = 1 ,506     ,23.747,24,25.1568
XS GIS Cut Line= 3
2308488.23869082346345.0030942082308448.65073645346434.291835158
2308313.94979883346738.103368659
#Sta/Elev= 30
       0  981.16   50.59  980.05    57.5  980.22 57.9712   979.9 63.0912  979.79
 68.8212  978.62 73.6112  978.37 80.2012  977.68 85.4512  974.99 88.6312  973.06
 92.4112  971.87 99.6712   970.3102.8812   970.2105.4312  974.73106.3012  975.21
114.9412  976.76137.1712  975.93166.5412  975.72201.0712  976.15238.5912  976.01
282.1312  976.81318.2412  977.18324.3312   978.3327.6312   978.5332.8312  978.52
336.1112  978.15340.2212  977.05395.7012  978.33402.3712  978.73430.0012  979.52
#Mann= 3 , 0 , 0
       0     .05       0 80.2012     .04       0114.9412     .05       0
Levee=0,,,-1,114.94,976.76,,
#XS Ineff= 2 , 0
       0                  117.92       0  978.24
Permanent Ineff=
       F       F
Bank Sta=80.2012,114.9412
XS Rating Curve= 0 ,0
Exp/Cntr=0.5,0.3

Type RM Length L Ch R = 1 ,494     ,121.8398,120,112.5147
XS GIS Cut Line= 3
2308455.09517482346390.5468380122308438.37323931346428.262365147
2308304.30304567346730.651285742
#Sta/Elev= 30
       0  980.12    7.48  979.96    9.11  979.63   13.75  977.63   24.34  976.61
   25.46  977.11   35.16  972.05   35.57  972.18   35.69  971.87   35.74  972.17
   37.63  970.85   41.24  970.02      44  969.97   48.07  971.65   48.66  972.65
   53.56  974.98   63.94   976.5  113.44  975.38     179  975.71  249.65  977.01
  264.69  976.97  264.91  979.06  280.06  977.68  293.33  978.37   302.8  978.27
  315.26  979.67  337.13  978.66  348.27  979.39  356.28  979.21  372.03  980.02
#Mann= 3 , 0 , 0
       0     .05       0   25.46     .04       0   63.94     .05       0
Levee=0,,,-1,63.94,976.5,,
#XS Ineff= 2 , 0
       0                   72.07       0  978.24
Permanent Ineff=
       F       F
Bank Sta=25.46,63.94
XS Rating Curve= 0 ,0
Exp/Cntr=0.3,0.1

Type RM Length L Ch R = 1 ,374     ,151.8259,150,139.392
XS GIS Cut Line= 3
2308471.19815934346082.8941238692308322.50264415 346437.54192285
2308238.87433086346637.000509087
#Sta/Elev= 30
       0  979.8823.53003  978.2984.96002  979.0793.10004  980.05  112.07  978.34
   168.7  978.08  242.19  978.58  263.88  979.98  285.57  978.53  299.12  976.59
  344.42  975.76  353.97  976.57361.5159  975.44374.2559  975.09379.5859   971.5
385.0559  970.47388.6659  970.92395.0959  975.92404.9359  975.76  428.46  978.57
  453.29  978.89  471.85  977.75  507.86  973.71  516.32  974.24  529.54  977.05
  556.65  976.22  568.83  979.06  581.26   978.9  591.89  977.57  600.84  979.86
#Mann= 3 , 0 , 0
       0     .05       0374.2559     .04       0395.0959     .05       0
Levee=-1,353.34,976.58,-1,445.16,978.88,,
Bank Sta=374.2559,395.0959
XS Rating Curve= 0 ,0
Exp/Cntr=0.3,0.1

Type RM Length L Ch R = 1 ,224     ,76.4313,74,65.5969
XS GIS Cut Line= 3
2308241.18936416 346001.204290782308204.57984033346349.556613945
2308177.94495832346602.996758849
#Sta/Elev= 30
       0  979.917.589966  977.68   15.13  977.0672.95001  977.1885.51996  980.41
95.62997  979.24  108.14  976.25  203.66  976.48  299.19   973.9  309.24  974.96
332.8518  974.79342.4818  975.45344.8418  971.15348.3318  969.97355.6718   971.1
362.0518   974.3370.7818  975.04384.3118     975  384.42  975.83  397.22  976.01
  442.47  975.23  467.61  976.04  487.72  975.67  515.37  973.33  525.45  974.21
  532.97  976.03  553.08  976.84  568.16  974.81  580.73  974.89  605.11  979.89
#Mann= 3 , 0 , 0
       0     .05       0342.4818     .04       0370.7818     .05       0
Levee=-1,342.48,975.45,-1,397.22,976.01,,
Bank Sta=342.4818,370.7818
XS Rating Curve= 0 ,0
Exp/Cntr=0.3,0.1

Type RM Length L Ch R = 1 ,150     ,0,0,0
XS GIS Cut Line= 4
2308038.67192539 346005.684673612308137.46841532346380.376476104
2308149.26523093346425.1166293962308132.85330057346581.281841857
#Sta/Elev= 30
       0   979.6   10.75  977.95   52.29  975.32    85.9  976.75  119.51  974.05
  132.44  978.26  142.78  978.92  173.81  975.04  178.98  973.62  188.75  974.72
  241.03  975.07  272.05  971.71  286.96  971.92  292.74  973.43  302.65   973.8
  308.25  972.71  341.86  975.28  375.86  975.03  382.12     971  389.05  969.67
  393.08  970.95  397.94  974.82  409.08  975.43  439.93  974.11  460.04  976.14
   507.8  973.19   525.4  976.94  548.02  975.25  562.65  975.36  590.79  979.85
#Mann= 3 , 0 , 0
       0     .05       0  375.86     .04       0  397.94     .05       0
Levee=-1,341.86,975.28,-1,409.08,975.43,,
Bank Sta=375.86,397.94
XS Rating Curve= 0 ,0
Exp/Cntr=0.3,0.1

Chan Stop Cuts=-1
Use User Specified Reach Order=0
Composite Channel Slope=5